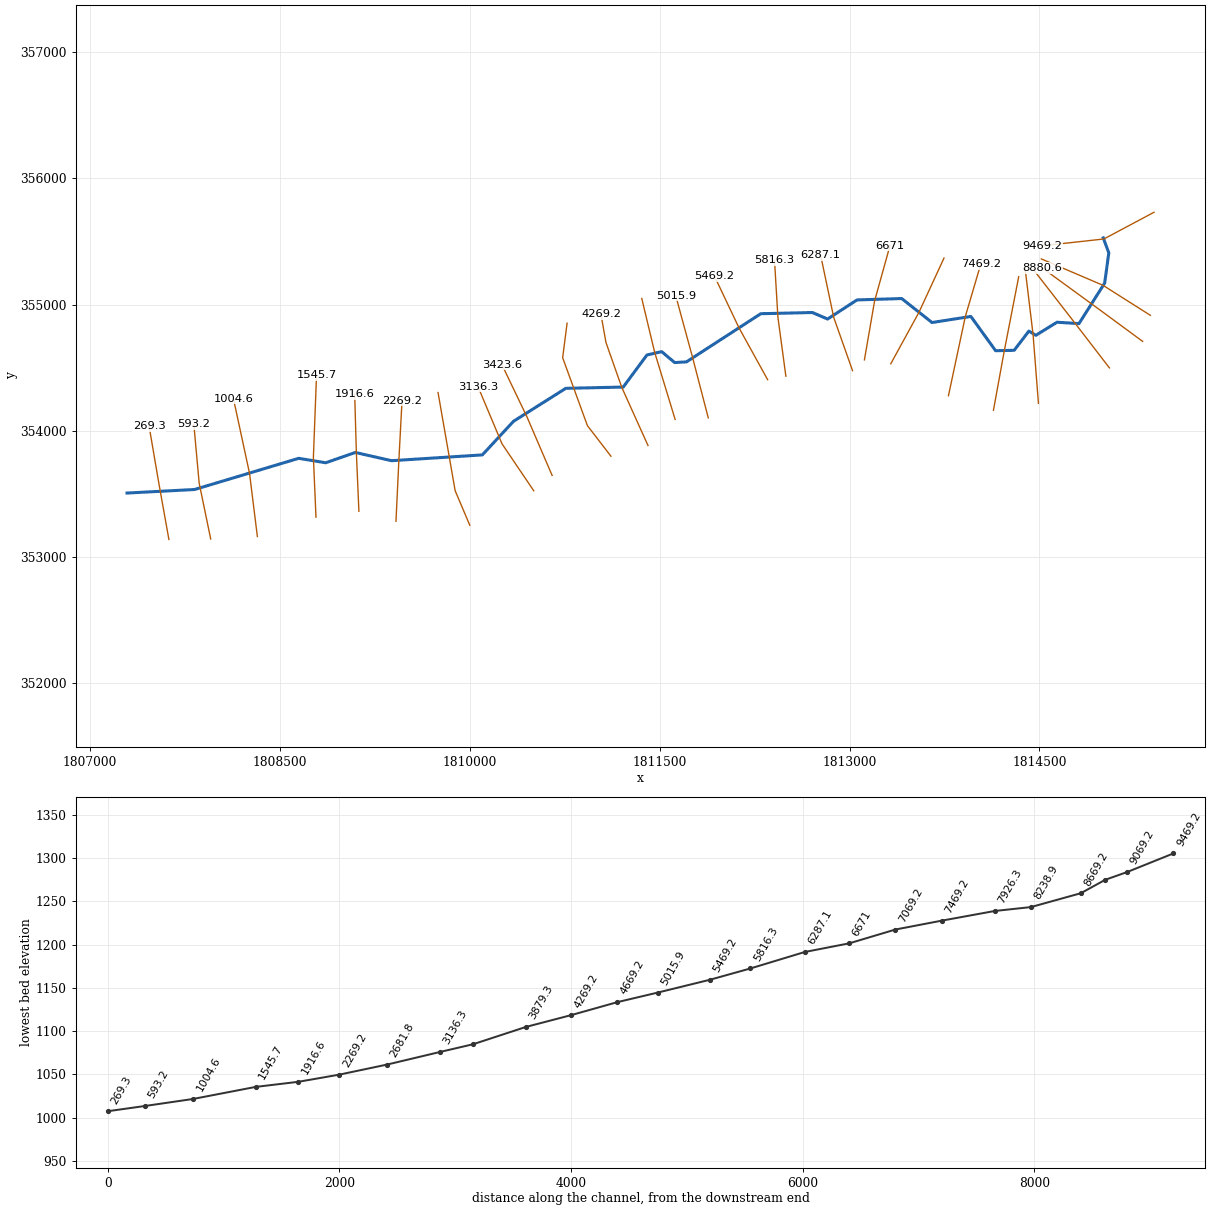
--- PnyCrk.prj (project) ---

Proj Title=PnyCrk
Current Plan=p01
Geom File=g01
Flow File=f01
Plan File=p01
DSS Export Rating Curves=0
DSS Export Rating Curve Sorted=0
DSS Export Volume Flow Curves=0
DXF OffsetX=0
DXF OffsetY=0
DXF ScaleX=0
DXF ScaleY=0

--- PnyCrk.p01 (plan) ---

Plan Title=Floodplain
Program Version=4.00
Geom File=g01
Flow File=f01
K Sum by GR=0
Std Step Tol=0.01
Critical Tol=0.01
Num of Std Step Trials=20
Max Error Tol=0.3
Flow Tol Ratio=0.001
Split Flow NTrial=30
Split Flow Tol=0.02
Split Flow Ratio=0.02
Log Output Level=0
Friction Slope Method=1
Unsteady Friction Slope Method=2
Unsteady Bridges Friction Slope Method=1
Global Log Level=0
CheckData=False
Run HTab=0
Run UNet=0
Run PostProcess=0
UNET Theta=0
UNET Theta Warmup=0
UNET ZTol=0
UNET ZSATol=0
UNET MxIter=0
UNET MaxInSteps=0
UNET DtIC=0
UNET DtMin=0
UNET MaxCRTS=0
UNET WFStab=0
UNET SFStab=0
UNET WFX=0
UNET SFX=0
UNET DSS MLevel=0
UNET DZMax Abort=0
UNET Convert EG Bridges=0
UNET Use Existing IB Tables=0
UNET Froude Limit=0
UNET Froude Power=0
Write IC File=0
Echo Input=False
Echo Output=False
Write Detailed=0

--- PnyCrk.f01 (steady flow) ---

Flow Title=NFF Regression Equation
Program Version=4.00
Number of Profiles=1
Profile Names=P100yr
River Rch & RM=PnyCrk,Main      ,9469.2
214.8917
River Rch & RM=PnyCrk,Main      ,9069.2
277.5550
River Rch & RM=PnyCrk,Main      ,8238.9
301.5807
River Rch & RM=PnyCrk,Main      ,7926.3
543.5229
River Rch & RM=PnyCrk,Main      ,6671
589.0941
River Rch & RM=PnyCrk,Main      ,6287.1
646.3527
River Rch & RM=PnyCrk,Main      ,5469.2
687.1114
River Rch & RM=PnyCrk,Main      ,5015.9
730.5429
River Rch & RM=PnyCrk,Main      ,3423.6
784.4978
River Rch & RM=PnyCrk,Main      ,2681.8
836.0263
River Rch & RM=PnyCrk,Main      ,269.3
918.6190
Boundary for River Rch & Prof#=PnyCrk,Main      ,1
Up Type=0
Dn Type=3
Dn Slope=0.027443

--- PnyCrk.g01 (geometry) ---

Geom Title=USGS 3m DEM
Program Version=4.00

River Reach=PnyCrk     ,Main
Reach XY= 30
     1815004.629      355528.187     1815048.442      355409.709
     1815015.712      355170.184     1814812.552      354849.382
     1814639.037      354860.326     1814471.687      354756.623
     1814416.711      354790.052     1814300.791      354638.106
     1814154.161      354634.662     1813958.334      354906.108
     1813651.528      354858.093     1813411.955      355047.868
     1813058.859      355037.024     1812826.330      354885.555
     1812706.636      354937.153     1812298.415      354927.819
     1811711.048      354546.396     1811618.211      354540.864
     1811515.062      354627.720     1811398.858      354600.901
     1811211.489      354346.952     1810757.776      354336.886
     1810344.664      354075.983     1810098.330      353809.649
     1809380.354      353763.830     1809094.823      353829.003
     1808860.854      353747.494     1808647.022      353782.546
     1807824.741      353535.807     1807290.646      353507.577

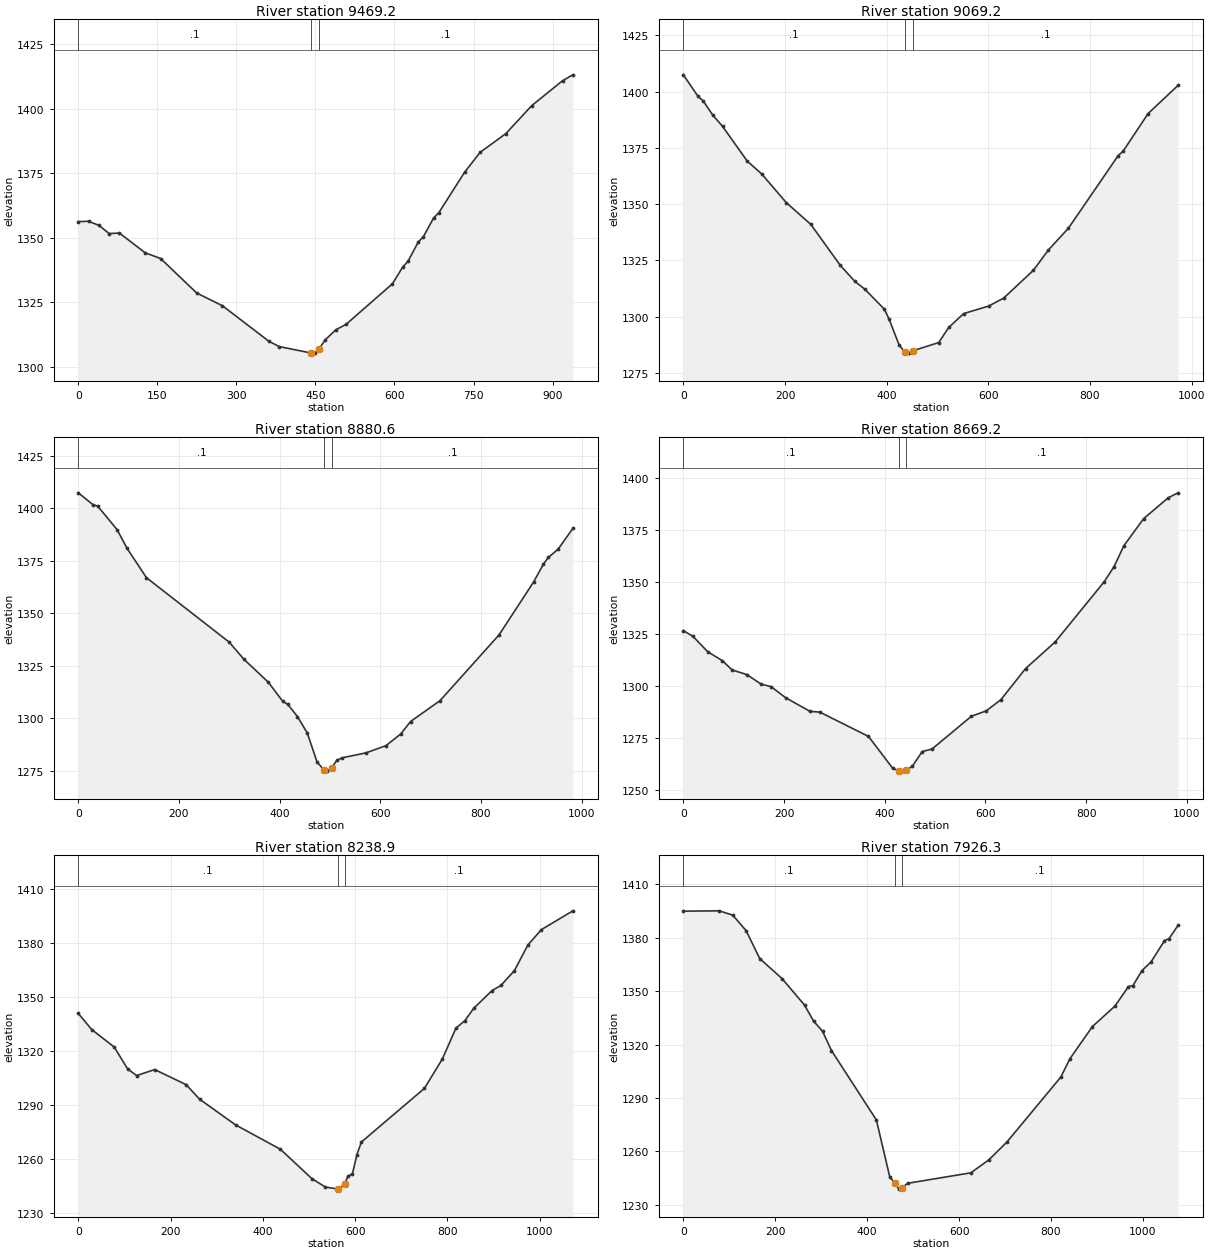
Type RM Length L Ch R = 1 ,9469.2,424.697,400,389.095
XS GIS Cut Line= 3
     1815405.995      355731.417     1815009.625      355519.552
     1814523.526      355465.827
#Sta/Elev= 30
       0 1356.26    19.5 1356.39    39.1 1354.82    58.6 1351.64    78.2 1351.82
   127.0 1344.17   156.3 1341.96   224.7 1328.59   273.6 1323.66   361.5 1309.92
   381.0 1307.86   441.9 1305.34   449.4 1305.30   456.9 1306.95   469.0 1310.54
   488.6 1314.32   508.1 1316.45   596.2 1332.18   615.7 1338.69   625.5 1340.84
   645.1 1348.35   654.8 1350.42   674.4 1357.72   684.2 1359.75   733.1 1375.41
   762.4 1383.08   811.3 1390.37   860.2 1401.17   918.9 1410.87   938.5 1413.15
#Mann= 3 , 0 , 0
       0     0.1       0   441.9   0.045       0   456.9     0.1       0
Bank Sta=   441.9,   456.9
Exp/Cntr=0.3,0.1

Type RM Length L Ch R = 1 ,9069.2,189.976,188.548,182.21
XS GIS Cut Line= 3
     1815376.645      354915.176     1815002.140      355152.917
     1814515.323      355361.574
#Sta/Elev= 30
       0 1407.44    28.9 1397.81    38.6 1395.94    57.9 1389.51    77.1 1384.53
   125.4 1369.15   154.3 1363.32   202.5 1350.63   250.7 1340.97   308.6 1322.79
   337.5 1315.61   356.8 1312.21   395.4 1303.28   405.0 1298.73   424.3 1287.43
   436.1 1284.08   443.6 1283.75   451.1 1284.76   502.4 1288.45   522.1 1295.17
   551.5 1301.33   600.5 1304.66   630.0 1308.17   688.8 1320.60   718.2 1329.59
   757.5 1339.25   855.5 1371.54   865.4 1373.56   914.4 1390.24   973.2 1402.73
#Mann= 3 , 0 , 0
       0     0.1       0   436.1   0.045       0   451.1     0.1       0
Bank Sta=   436.1,   451.1
Exp/Cntr=0.3,0.1

Type RM Length L Ch R = 1 ,8880.6,216.302,211.452,214.467
XS GIS Cut Line= 3
     1815315.706      354708.708     1814965.304      354967.022
     1814523.523      355289.757
#Sta/Elev= 30
       0 1407.40    29.0 1401.81    38.7 1401.03    77.4 1389.77    96.7 1381.03
   135.4 1366.98   299.9 1336.24   328.9 1328.13   377.3 1317.22   406.3 1308.01
   416.0 1306.68   435.3 1300.84   454.9 1292.96   474.4 1279.08   488.6 1275.31
   493.9 1274.82   503.6 1276.51   513.5 1279.95   523.3 1281.11   572.1 1283.56
   611.2 1286.97   640.5 1292.53   660.0 1298.45   718.6 1308.41   835.9 1339.77
   904.3 1364.89   923.8 1373.38   933.6 1376.60   953.1 1380.55   982.4 1390.44
#Mann= 3 , 0 , 0
       0     0.1       0   488.6   0.045       0   503.6     0.1       0
Bank Sta=   488.6,   503.6
Exp/Cntr=0.3,0.1

Type RM Length L Ch R = 1 ,8669.2,429.177,430.31,407.008
XS GIS Cut Line= 3
     1815053.195      354498.746     1814788.116      354844.059
     1814453.094      355276.596
#Sta/Elev= 30
       0 1326.77    19.3 1323.96    48.4 1316.58    77.4 1312.35    96.7 1307.89
   125.8 1305.67   154.8 1301.02   174.1 1299.87   203.2 1294.51   251.5 1287.97
   270.9 1287.63   367.6 1275.95   416.0 1260.56   427.8 1259.51   435.3 1259.27
   442.8 1259.61   454.9 1261.67   474.4 1268.67   493.9 1269.90   572.1 1285.65
   601.4 1288.20   630.7 1293.61   679.6 1308.54   738.2 1321.27   835.9 1350.26
   855.4 1357.54   875.0 1367.60   914.0 1380.53   962.9 1390.58   982.4 1392.97
#Mann= 3 , 0 , 0
       0     0.1       0   427.8   0.045       0   442.8     0.1       0
Bank Sta=   427.8,   442.8
Exp/Cntr=0.3,0.1

Type RM Length L Ch R = 1 ,8238.9,333.18,312.621,301.825
XS GIS Cut Line= 3
     1814492.357      354218.327     1814450.056      354762.032
     1814387.200      355284.921
#Sta/Elev= 30
       0 1341.01    29.2 1332.01    77.9 1322.31   107.1 1310.10   126.6 1306.45
   165.6 1309.77   233.7 1301.40   262.9 1293.30   340.8 1279.03   438.2 1265.43
   506.4 1249.08   535.6 1244.44   562.2 1243.37   564.9 1243.28   577.2 1246.02
   584.4 1250.44   594.1 1251.74   603.9 1262.39   613.6 1269.46   750.2 1299.31
   789.2 1315.69   818.4 1332.73   837.9 1337.00   857.4 1343.93   896.5 1353.64
   916.0 1356.56   945.2 1364.76   974.5 1379.06  1003.7 1387.60  1072.0 1398.06
#Mann= 3 , 0 , 0
       0     0.1       0   562.2   0.045       0   577.2     0.1       0
Bank Sta=   562.2,   577.2
Exp/Cntr=0.3,0.1

Type RM Length L Ch R = 1 ,7926.3,458.355,457.069,454.261
XS GIS Cut Line= 3
     1814136.826      354163.245     1814220.747      354624.359
     1814336.456      355220.856
#Sta/Elev= 30
       0 1394.98    78.1 1395.16   107.4 1392.74   136.7 1383.94   166.0 1368.36
   214.8 1357.04   263.6 1342.19   283.2 1333.22   302.7 1327.51   322.2 1316.65
   419.9 1277.64   449.2 1245.48   460.6 1242.18   468.7 1238.76   475.6 1239.64
   488.3 1242.06   625.5 1247.92   664.7 1255.21   703.9 1265.20   821.5 1301.80
   841.1 1312.05   890.1 1330.14   939.1 1341.64   968.5 1352.59   978.3 1353.17
   997.9 1361.61  1017.5 1366.39  1046.9 1378.39  1056.7 1379.49  1076.3 1386.94
#Mann= 3 , 0 , 0
       0     0.1       0   460.6   0.045       0   475.6     0.1       0
Bank Sta=   460.6,   475.6
Exp/Cntr=0.3,0.1

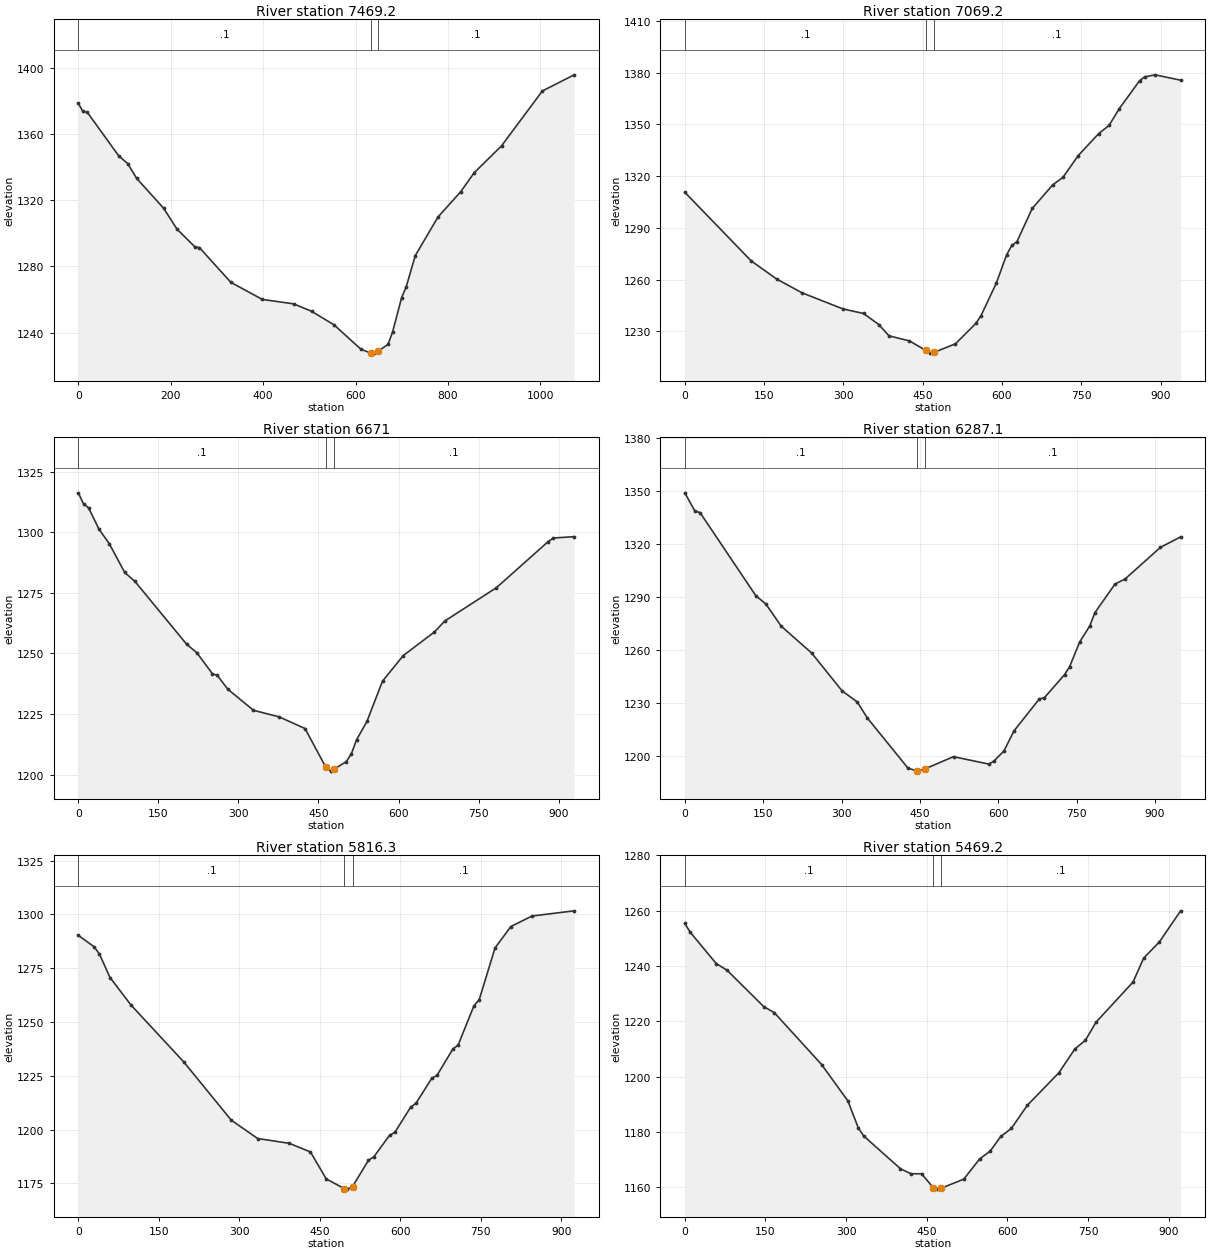
Type RM Length L Ch R = 1 ,7469.2,405.839,400,397.606
XS GIS Cut Line= 3
     1813781.294      354278.417     1813914.565      354905.261
     1814036.676      355319.973
#Sta/Elev= 30
       0 1378.61     9.7 1373.74    19.4 1373.17    87.4 1346.87   106.8 1342.19
   126.2 1333.25   184.5 1315.23   213.6 1302.54   252.5 1291.80   262.2 1291.36
   330.1 1270.39   398.1 1260.07   466.1 1257.36   504.9 1252.87   553.5 1244.69
   611.7 1229.90   633.4 1227.61   640.9 1227.59   648.4 1228.61   670.3 1232.89
   680.2 1240.36   699.8 1261.17   709.6 1267.59   729.3 1286.53   778.4 1309.84
   827.5 1325.11   857.0 1336.69   916.0 1352.89  1004.4 1386.07  1073.2 1395.83
#Mann= 3 , 0 , 0
       0     0.1       0   633.4   0.045       0   648.4     0.1       0
Bank Sta=   633.4,   648.4
Exp/Cntr=0.3,0.1

Type RM Length L Ch R = 1 ,7069.2,390.747,398.159,401.042
XS GIS Cut Line= 3
     1813325.391      354530.989     1813547.761      354937.798
     1813746.276      355368.522
#Sta/Elev= 30
       0 1310.66   125.6 1270.83   173.9 1260.28   222.2 1252.27   299.4 1242.96
   338.1 1240.35   367.0 1233.89   386.3 1227.37   425.0 1224.42   456.1 1218.89
   463.6 1217.34   471.1 1217.73   512.0 1222.76   550.7 1234.62   560.4 1239.12
   589.4 1258.03   608.8 1274.38   618.5 1279.83   628.2 1281.96   657.2 1301.27
   695.9 1314.93   715.3 1319.31   744.3 1331.96   783.0 1344.71   802.4 1349.39
   821.7 1359.08   860.5 1375.48   870.1 1377.59   889.5 1378.78   937.9 1375.67
#Mann= 3 , 0 , 0
       0     0.1       0   456.1   0.045       0   471.1     0.1       0
Bank Sta=   456.1,   471.1
Exp/Cntr=0.3,0.1

Type RM Length L Ch R = 1 ,6671,373.728,383.945,394.6
XS GIS Cut Line= 3
     1813117.253      354562.148     1813197.617      355028.224
     1813319.624      355467.739
#Sta/Elev= 30
       0 1316.32     9.7 1311.76    19.3 1310.09    38.6 1301.35    57.9 1295.35
    86.9 1283.43   106.2 1279.71   202.7 1253.86   222.0 1250.31   251.0 1241.67
   260.6 1240.89   279.9 1235.27   328.2 1226.52   376.4 1223.79   424.7 1219.00
   463.5 1203.14   473.0 1201.40   478.5 1202.14   502.1 1205.30   511.8 1208.67
   521.5 1214.39   540.9 1221.98   570.0 1238.57   608.8 1249.10   667.1 1258.83
   686.5 1263.36   783.5 1277.16   880.6 1296.22   890.3 1297.66   929.1 1298.22
#Mann= 3 , 0 , 0
       0     0.1       0   463.5   0.045       0   478.5     0.1       0
Bank Sta=   463.5,   478.5
Exp/Cntr=0.3,0.1

Type RM Length L Ch R = 1 ,6287.1,476.286,470.774,467.669
XS GIS Cut Line= 3
     1813023.449      354477.069     1812874.835      354898.253
     1812771.621      355389.943
#Sta/Elev= 30
       0 1348.92    19.4 1338.57    29.1 1337.76   135.9 1290.73   155.4 1285.90
   184.5 1273.46   242.7 1258.27   301.0 1236.85   330.1 1230.54   349.5 1221.43
   427.2 1193.08   444.7 1191.45   446.6 1191.39   459.7 1192.66   514.3 1199.57
   581.9 1195.38   591.6 1197.04   610.9 1202.87   630.2 1214.22   678.5 1232.25
   688.2 1232.93   726.8 1245.99   736.5 1250.51   755.8 1264.48   775.1 1273.55
   784.8 1281.03   823.4 1297.28   842.8 1300.18   910.4 1318.06   949.0 1323.98
#Mann= 3 , 0 , 0
       0     0.1       0   444.7   0.045       0   459.7     0.1       0
Bank Sta=   444.7,   459.7
Exp/Cntr=0.3,0.1

Type RM Length L Ch R = 1 ,5816.3,337.033,347.122,355.667
XS GIS Cut Line= 3
     1812496.622      354433.085     1812433.702      354900.639
     1812406.857      355351.727
#Sta/Elev= 30
       0 1290.26    29.5 1284.92    39.3 1281.58    59.0 1270.67    98.3 1257.82
   196.6 1231.38   285.0 1204.33   334.2 1195.83   393.1 1193.60   432.5 1189.58
   461.9 1177.05   495.8 1172.51   501.2 1172.31   510.8 1173.51   540.5 1185.71
   550.4 1187.32   579.8 1197.30   589.7 1198.70   619.1 1210.40   628.9 1212.18
   658.4 1223.81   668.2 1225.20   697.7 1237.43   707.5 1239.24   737.0 1257.52
   746.8 1260.37   776.3 1284.40   805.8 1294.37   845.1 1299.24   923.7 1301.66
#Mann= 3 , 0 , 0
       0     0.1       0   495.8   0.045       0   510.8     0.1       0
Bank Sta=   495.8,   510.8
Exp/Cntr=0.3,0.1

Type RM Length L Ch R = 1 ,5469.2,459.519,453.325,448.674
XS GIS Cut Line= 3
     1812352.588      354405.218     1812126.024      354816.529
     1811932.277      355225.371
#Sta/Elev= 30
       0 1255.35     9.8 1252.22    58.7 1240.79    78.3 1238.49   146.7 1225.30
   166.3 1223.12   254.4 1204.36   303.3 1191.20   322.8 1181.39   332.6 1178.56
   401.1 1166.69   420.7 1164.89   440.2 1164.89   462.1 1159.88   469.6 1159.34
   477.1 1159.69   518.8 1162.96   548.3 1170.25   567.9 1173.09   587.6 1178.36
   607.3 1181.30   636.8 1189.59   695.8 1201.42   725.3 1209.98   745.0 1213.13
   764.6 1219.63   833.5 1234.16   853.2 1242.77   882.7 1248.70   922.0 1259.89
#Mann= 3 , 0 , 0
       0     0.1       0   462.1   0.045       0   477.1     0.1       0
Bank Sta=   462.1,   477.1
Exp/Cntr=0.3,0.1

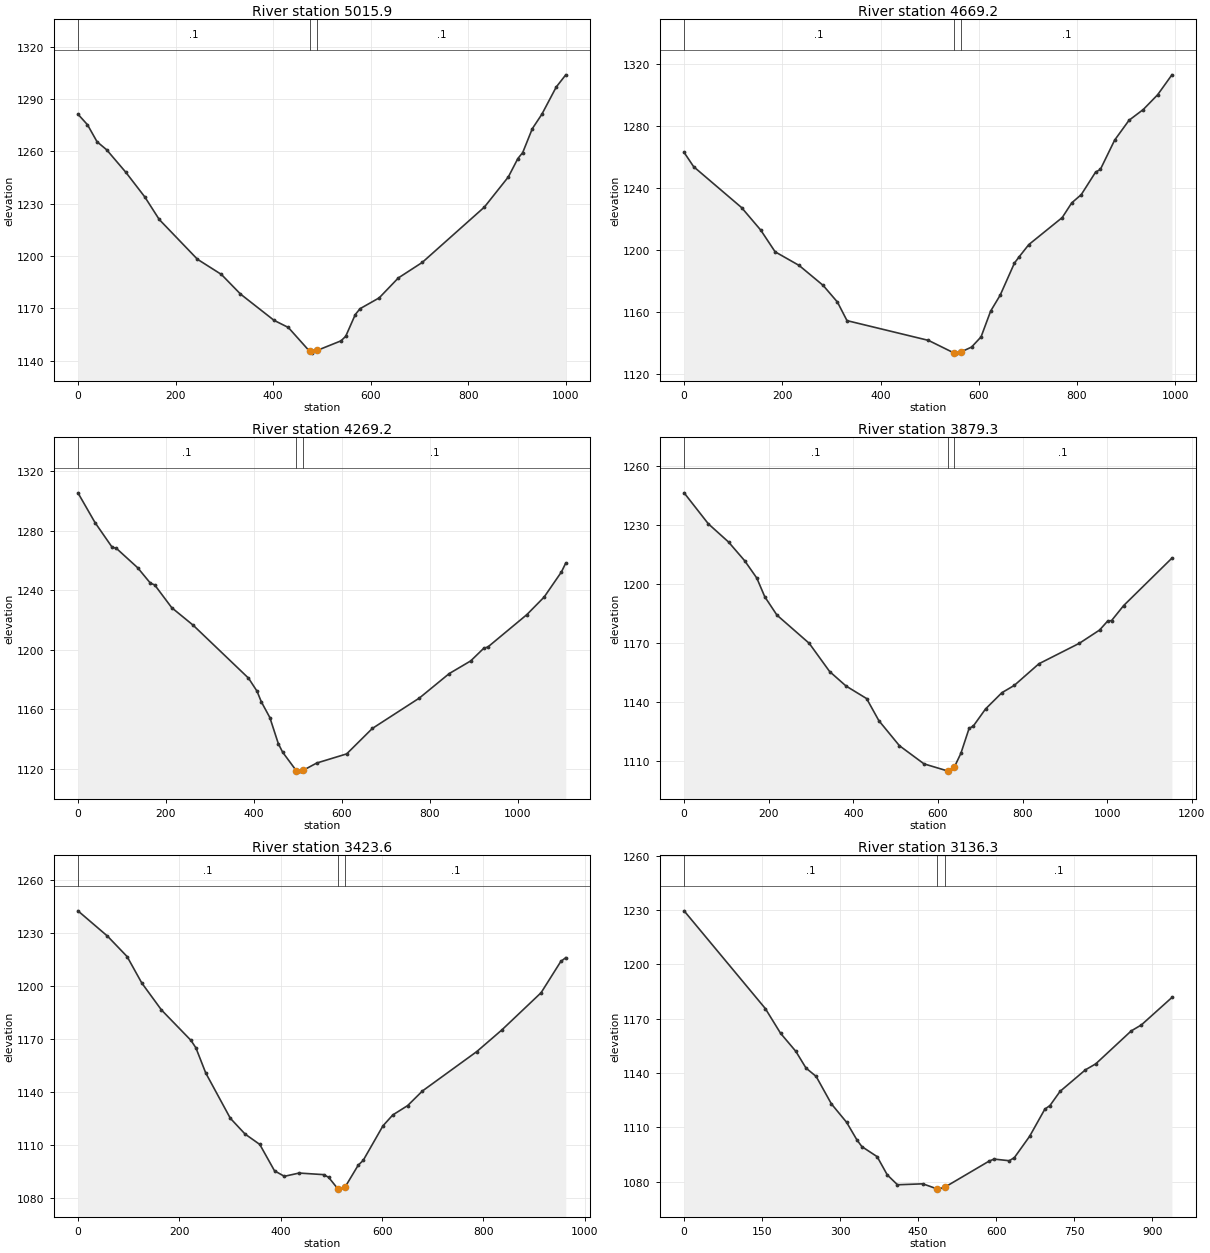
Type RM Length L Ch R = 1 ,5015.9,345.354,346.675,346.627
XS GIS Cut Line= 3
     1811883.458      354103.155     1811755.512      354596.287
     1811626.651      355069.154
#Sta/Elev= 30
       0 1281.32    19.6 1275.24    39.2 1265.50    58.8 1260.93    98.0 1248.07
   137.2 1233.83   166.6 1220.98   244.9 1198.19   293.9 1189.51   333.1 1178.26
   401.7 1163.23   431.1 1159.12     475 1145.39   480.1 1144.42     490 1145.95
   538.9 1151.44   548.7 1154.06   568.3 1166.52   578.1 1169.88   617.3 1176.08
   656.5 1187.49   705.5 1196.37   832.9 1228.10   881.9 1245.35   901.5 1255.91
   911.4 1259.33   931.0 1272.98   950.6 1281.26   980.0 1296.83   999.6 1303.85
#Mann= 3 , 0 , 0
       0     0.1       0     475   0.045       0     490     0.1       0
Bank Sta=     475,     490
Exp/Cntr=0.3,0.1

Type RM Length L Ch R = 1 ,4669.2,397.259,400,402.182
XS GIS Cut Line= 3
     1811621.577      354090.960     1811459.668      354623.026
     1811358.030      355048.195
#Sta/Elev= 30
       0 1262.78    19.5 1253.56   117.1 1227.22   156.1 1212.70   185.4 1198.72
   234.2 1189.95   283.0 1177.13   312.2 1166.37   331.7 1154.39   497.6 1141.66
   548.7 1133.69   556.2 1133.45   563.7 1134.21   585.3 1137.34   604.7 1143.93
   624.2 1160.54   643.6 1170.78   672.7 1191.51   682.4 1195.57   701.9 1203.38
   769.9 1220.78   789.3 1230.26   808.7 1235.58   837.9 1250.09   847.6 1251.81
   876.7 1270.70   905.9 1283.46   935.0 1290.42   964.2 1299.91   993.3 1312.76
#Mann= 3 , 0 , 0
       0     0.1       0   548.7   0.045       0   563.7     0.1       0
Bank Sta=   548.7,   563.7
Exp/Cntr=0.3,0.1

Type RM Length L Ch R = 1 ,4269.2,391.558,389.9,390.168
XS GIS Cut Line= 4
     1811407.278      353883.921     1811200.435      354343.402
     1811074.906      354700.766     1811035.472      354923.286
#Sta/Elev= 30
       0 1305.61    38.8 1285.62    77.5 1269.10    87.2 1268.30   135.7 1255.23
   164.7 1244.83   174.4 1243.67   213.2 1228.33   261.6 1216.62   387.6 1180.95
   407.0 1172.16   416.7 1165.05   436.1 1154.45   455.4 1136.87   465.1 1131.18
   496.4 1118.63   503.9 1118.39   511.4 1118.88   542.7 1123.84   610.7 1129.98
   669.0 1147.09   775.8 1167.53   843.8 1184.02   892.5 1192.52   922.0 1200.97
   931.8 1201.95  1020.2 1223.68  1059.5 1235.51  1098.8 1252.41  1108.6 1258.39
#Mann= 3 , 0 , 0
       0     0.1       0   496.4   0.045       0   511.4     0.1       0
Bank Sta=   496.4,   511.4
Exp/Cntr=0.3,0.1

Type RM Length L Ch R = 1 ,3879.3,453.689,455.685,457.97
XS GIS Cut Line= 4
     1811114.340      353799.420     1810928.437      354041.657
     1810732.916      354579.301     1810767.885      354852.869
#Sta/Elev= 30
       0 1246.40    57.3 1230.63   105.0 1221.39   143.1 1211.87   171.8 1203.06
   190.8 1193.48   219.5 1184.17   295.8 1169.81   344.1 1155.44   382.9 1148.07
   431.4 1141.70   460.5 1130.43   509.0 1117.71   567.2 1108.45   624.2 1104.77
   625.3 1104.76   639.2 1106.96   654.4 1113.86   673.8 1126.55   683.5 1127.64
   712.6 1136.40   751.4 1144.70   780.5 1148.38   838.7 1159.39   934.5 1169.84
   982.1 1176.55  1001.1 1181.10  1010.6 1181.40  1039.1 1189.02  1153.2 1213.16
#Mann= 3 , 0 , 0
       0     0.1       0   624.2   0.045       0   639.2     0.1       0
Bank Sta=   624.2,   639.2
Exp/Cntr=0.3,0.1

Type RM Length L Ch R = 1 ,3423.6,289.804,287.348,284.361
XS GIS Cut Line= 3
     1810649.583      353647.317     1810450.884      354110.694
     1810253.177      354523.938
#Sta/Elev= 30
       0 1242.48    58.2 1228.17    97.0 1216.56   126.0 1201.56   164.8 1186.30
   223.0 1169.06   232.7 1164.85   252.1 1150.61   300.6 1124.94   329.7 1116.00
   358.7 1110.12   387.8 1095.16   407.2 1092.05   436.3 1093.90   484.8 1093.00
   494.5 1091.48   512.3 1085.13   513.9 1084.79   527.3 1086.12   552.9 1098.37
   562.7 1101.07   601.7 1120.65   621.1 1126.83   650.4 1132.12   679.6 1140.41
   786.8 1162.74   835.6 1174.83   913.6 1196.07   952.5 1213.80   962.3 1215.94
#Mann= 3 , 0 , 0
       0     0.1       0   512.3   0.045       0   527.3     0.1       0
Bank Sta=   512.3,   527.3
Exp/Cntr=0.3,0.1

Type RM Length L Ch R = 1 ,3136.3,457.943,454.429,451.156
XS GIS Cut Line= 3
     1810504.515      353525.569     1810253.408      353897.926
     1810064.705      354348.343
#Sta/Elev= 30
       0 1229.51   156.2 1175.50   185.5 1161.84   214.8 1151.88   234.3 1142.66
   253.8 1138.04   283.1 1122.88   312.4 1112.67   332.0 1103.04   341.7 1099.27
   371.0 1093.73   390.5 1083.65   410.1 1078.20   458.9 1078.72   486.6 1075.87
   488.2 1075.79   501.6 1076.95   585.9 1091.22   595.6 1092.38   624.9 1091.48
   634.7 1093.18   664.0 1104.95   693.3 1119.98   703.1 1121.95   722.6 1129.81
   771.4 1141.71   791.0 1144.96   859.3 1163.18   878.9 1166.51   937.5 1181.64
#Mann= 3 , 0 , 0
       0     0.1       0   486.6   0.045       0   501.6     0.1       0
Bank Sta=   486.6,   501.6
Exp/Cntr=0.3,0.1

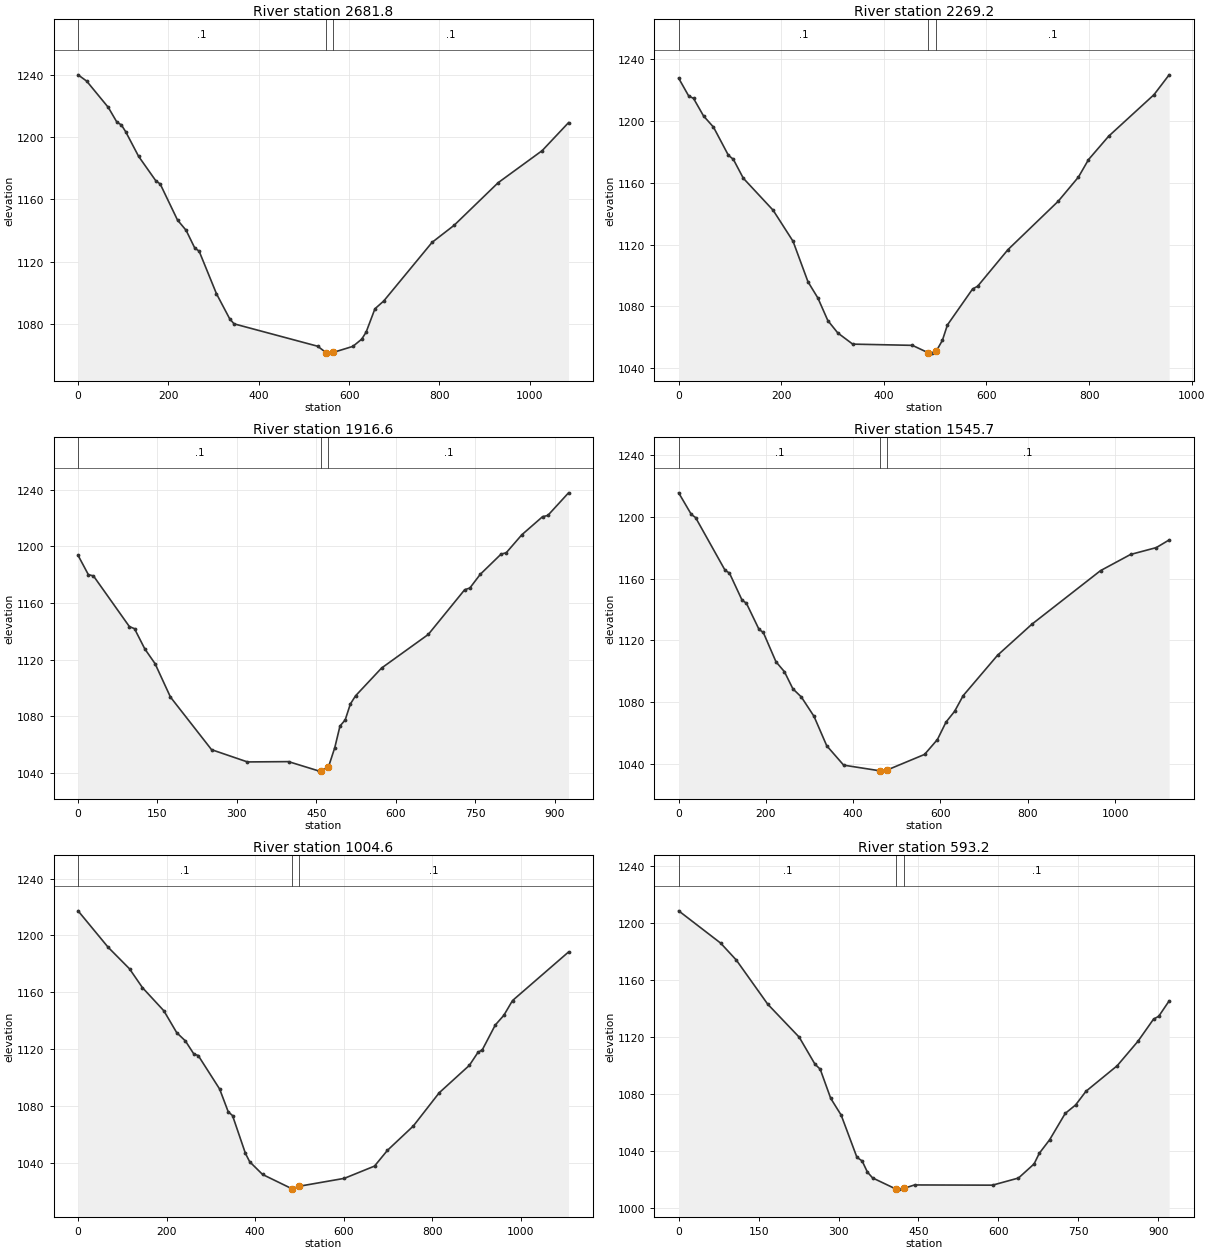
Type RM Length L Ch R = 1 ,2681.8,418.784,412.639,406.829
XS GIS Cut Line= 3
     1809998.924      353252.978     1809883.438      353526.199
     1809748.236      354303.611
#Sta/Elev= 30
       0 1239.85    19.1 1235.81    67.0 1218.91    86.1 1209.42    95.7 1207.78
   105.3 1203.41   134.0 1187.56   172.2 1171.84   181.8 1169.83   220.1 1146.70
   239.2 1140.09   258.4 1128.69   267.9 1126.78   306.4 1099.39   335.6 1083.35
   345.3 1080.10   530.4 1065.73   549.7 1061.47   559.7 1061.31   564.7 1061.75
   608.4 1065.65   627.8 1070.27   637.6 1074.75   657.1 1089.75   676.6 1094.75
   783.7 1132.39   832.4 1143.31   929.8 1170.63  1027.3 1191.22  1085.7 1209.19
#Mann= 3 , 0 , 0
       0     0.1       0   549.7   0.045       0   564.7     0.1       0
Bank Sta=   549.7,   564.7
Exp/Cntr=0.3,0.1

Type RM Length L Ch R = 1 ,2269.2,349.115,352.577,355.272
XS GIS Cut Line= 3
     1809415.865      353283.962     1809439.210      353777.828
     1809463.749      354238.826
#Sta/Elev= 30
       0 1227.74    19.4 1216.31    29.1 1214.61    48.5 1203.29    67.9 1196.05
    96.9 1177.84   106.6 1175.20   126.0 1162.97   184.2 1142.20   223.0 1122.10
   252.1 1095.87   271.4 1085.37   290.8 1070.75   310.2 1062.74   339.3 1055.50
   455.6 1054.71   486.9 1049.83   494.4 1049.67   501.9 1050.81   514.1 1057.96
   523.9 1067.92   573.0 1091.24   582.8 1092.99   641.8 1116.66   740.0 1148.09
   779.3 1163.71   798.9 1175.00   838.2 1190.17   926.6 1217.07   956.1 1229.92
#Mann= 3 , 0 , 0
       0     0.1       0   486.9   0.045       0   501.9     0.1       0
Bank Sta=   486.9,   501.9
Exp/Cntr=0.3,0.1

Type RM Length L Ch R = 1 ,1916.6,370.454,370.925,370.451
XS GIS Cut Line= 3
     1809122.912      353363.510     1809102.454      353838.118
     1809089.639      354289.297
#Sta/Elev= 30
       0 1193.60    19.4 1180.01    29.1 1179.09    96.9 1143.37   106.6 1141.88
   126.0 1127.65   145.4 1117.23   174.5 1093.64   252.1 1056.54   319.9 1047.89
   397.5 1048.10   455.7 1041.40   457.9 1041.40   472.9 1044.28   484.9 1058.02
   494.7 1073.22   504.5 1077.48   514.3 1088.75   524.1 1094.52   573.2 1114.09
   661.5 1137.82   730.2 1169.35   740.0 1170.57   759.6 1180.20   798.9 1194.45
   808.7 1195.43   838.1 1208.10   877.3 1220.87   887.2 1221.73   926.4 1237.70
#Mann= 3 , 0 , 0
       0     0.1       0   457.9   0.045       0   472.9     0.1       0
Bank Sta=   457.9,   472.9
Exp/Cntr=0.3,0.1

Type RM Length L Ch R = 1 ,1545.7,539.298,541.121,545.175
XS GIS Cut Line= 3
     1808783.756      353316.545     1808763.297      353791.153
     1808788.054      354439.643
#Sta/Elev= 30
       0 1215.42    29.1 1201.41    38.8 1199.42   106.6 1165.21   116.3 1163.59
   145.4 1145.95   155.1 1144.10   184.2 1127.09   193.9 1125.18   223.0 1106.19
   242.4 1099.73   261.8 1088.66   281.2 1083.38   310.2 1070.87   339.3 1051.87
   378.1 1039.32     462 1035.62   465.4 1035.45     477 1036.09   563.5 1046.25
   593.0 1055.88   612.7 1067.18   632.4 1074.13   652.0 1084.27   730.7 1110.36
   809.4 1130.44   966.7 1165.09  1035.5 1175.55  1094.5 1179.99  1124.0 1184.95
#Mann= 3 , 0 , 0
       0     0.1       0     462   0.045       0     477     0.1       0
Bank Sta=     462,     477
Exp/Cntr=0.3,0.1

Type RM Length L Ch R = 1 ,1004.6,409.589,411.363,412.282
XS GIS Cut Line= 3
     1808320.666      353163.442     1808258.683      353663.593
     1808131.722      354254.014
#Sta/Elev= 30
       0 1217.31    67.8 1191.72   116.3 1176.49   145.4 1163.28   193.8 1146.97
   222.9 1131.55   242.3 1125.82   261.7 1116.51   271.4 1115.51   319.8 1091.91
   339.2 1075.89   348.9 1073.26   378.0 1046.67   387.7 1040.74   416.8 1031.81
   483.6 1021.69   484.6 1021.50   498.6 1023.48   601.4 1029.08   669.6 1037.70
   698.8 1048.79   757.2 1065.90   815.7 1089.28   883.9 1108.61   903.3 1117.72
   913.1 1119.52   942.3 1136.92   961.8 1143.82   981.3 1154.16  1107.9 1188.36
#Mann= 3 , 0 , 0
       0     0.1       0   483.6   0.045       0   498.6     0.1       0
Bank Sta=   483.6,   498.6
Exp/Cntr=0.3,0.1

Type RM Length L Ch R = 1 ,593.2,324.501,323.894,323.286
XS GIS Cut Line= 3
     1807951.917      353143.856     1807860.599      353587.103
     1807818.518      354053.013
#Sta/Elev= 30
       0 1208.43    78.7 1185.85   108.2 1173.94   167.2 1143.01   226.3 1119.88
   255.8 1101.00   265.6 1097.50   285.3 1077.10   305.0 1065.28   334.5 1035.78
   344.3 1033.20   354.2 1025.39   364.0 1021.31   407.8 1013.52   413.2 1013.47
   422.8 1014.02   442.7 1016.40   589.0 1016.25   637.7 1021.25   667.0 1031.14
   676.7 1038.56   696.2 1048.09   725.4 1066.51   744.9 1072.44   764.4 1082.05
   822.9 1099.91   861.9 1117.07   891.1 1132.55   900.9 1134.58   920.4 1145.34
#Mann= 3 , 0 , 0
       0     0.1       0   407.8   0.045       0   422.8     0.1       0
Bank Sta=   407.8,   422.8
Exp/Cntr=0.3,0.1

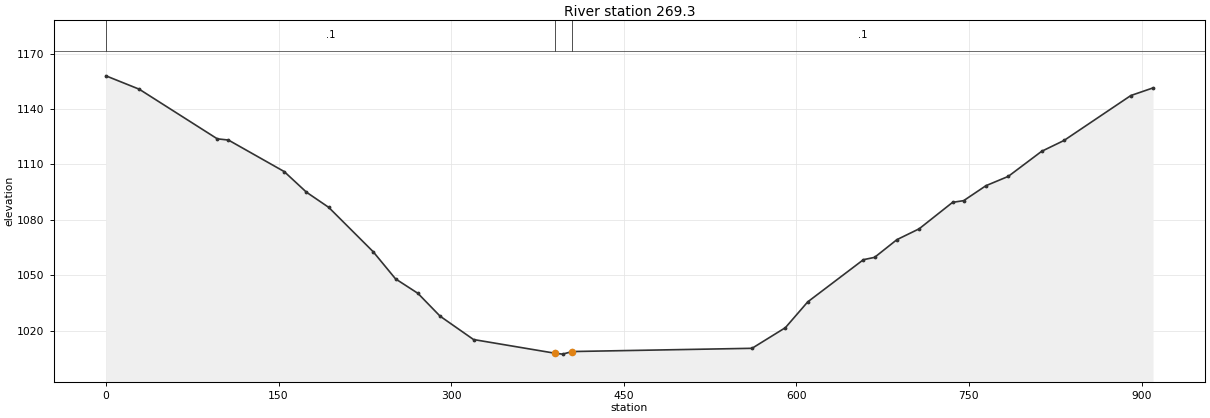
Type RM Length L Ch R = 1 ,269.3,285.926,269.309,252.693
XS GIS Cut Line= 3
     1807621.616      353139.954     1807541.601      353587.856
     1807465.203      354036.437
#Sta/Elev= 30
       0 1157.97    29.0 1150.72    96.8 1123.88   106.5 1123.21   154.9 1106.18
   174.3 1094.99   193.6 1086.81   232.3 1062.77   251.7 1048.10   271.1 1040.29
   290.4 1027.92   319.5 1015.26   390.3 1007.85   396.9 1007.37   405.3 1008.77
   561.5 1010.52   590.5 1021.69   609.9 1035.65   658.3 1058.48   668.0 1059.73
   687.4 1069.32   706.7 1075.17   735.8 1089.51   745.4 1090.42   764.8 1098.52
   784.2 1103.56   813.2 1117.13   832.6 1122.98   890.7 1147.31   910.0 1151.44
#Mann= 3 , 0 , 0
       0     0.1       0   390.3   0.045       0   405.3     0.1       0
Bank Sta=   390.3,   405.3
Exp/Cntr=0.3,0.1